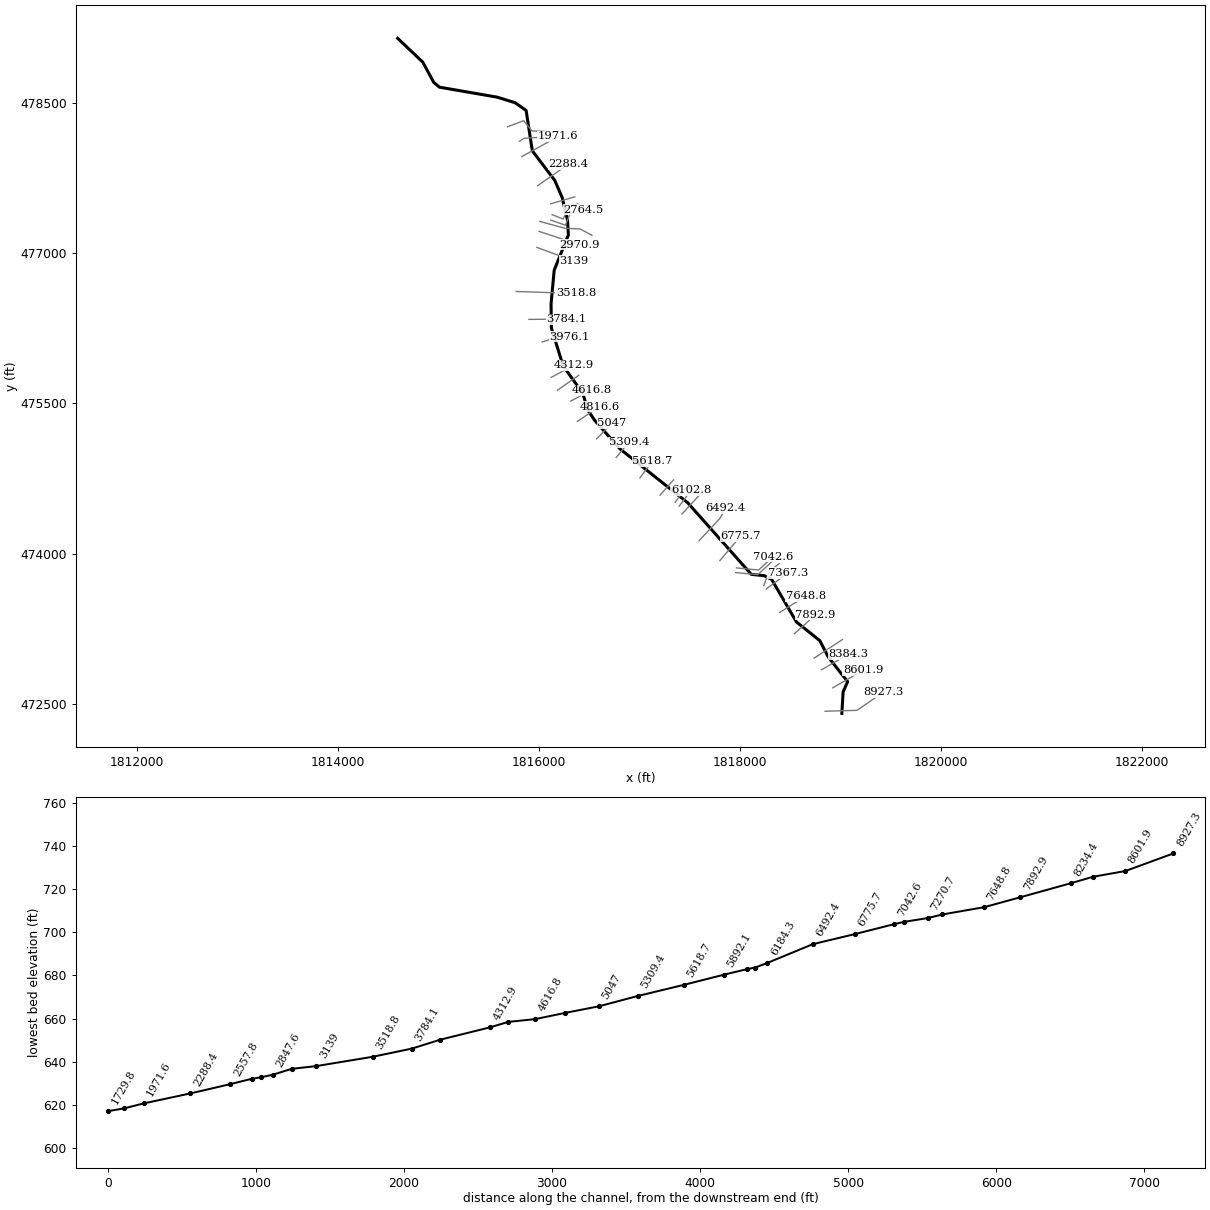
--- SPRINGFORK.prj (project) ---

Proj Title=SPRINGFORK
Current Plan=p01
Default Exp/Contr=0,0
English Units
Geom File=g01
Flow File=f01
Plan File=p01
BEGIN DESCRIPTION:
END DESCRIPTION:
DSS Export Rating Curves= 0
DSS Export Rating Curve Sorted= 0
DSS Export Volume Flow Curves= 0
DXF OffsetX= 0
DXF OffsetY= 0
DXF ScaleX= 0
DXF ScaleY= 0

--- SPRINGFORK.p01 (plan) ---

Plan Title=Floodplain
Program Version=4.00
Geom File=g01
Flow File=f01
K Sum by GR=0
Std Step Tol=0.01
Critical Tol=0.01
Num of Std Step Trials=20
Max Error Tol=0.3
Flow Tol Ratio=0.001
Split Flow NTrial=30
Split Flow Tol=0.02
Split Flow Ratio=0.02
Log Output Level=0
Friction Slope Method=1
Unsteady Friction Slope Method=2
Unsteady Bridges Friction Slope Method=1
Global Log Level=0
CheckData=False
Run HTab=0
Run UNet=0
Run PostProcess=0
UNET Theta=0
UNET Theta Warmup=0
UNET ZTol=0
UNET ZSATol=0
UNET MxIter=0
UNET MaxInSteps=0
UNET DtIC=0
UNET DtMin=0
UNET MaxCRTS=0
UNET WFStab=0
UNET SFStab=0
UNET WFX=0
UNET SFX=0
UNET DSS MLevel=0
UNET DZMax Abort=0
UNET Convert EG Bridges=0
UNET Use Existing IB Tables=0
UNET Froude Limit=0
UNET Froude Power=0
Write IC File=0
Echo Input=False
Echo Output=False
Write Detailed=0

--- SPRINGFORK.f01 (steady flow) ---

Flow Title=NFF Regression Equation
Program Version=4.10
Number of Profiles= 1
Profile Names=P100yr
River Rch & RM=SPRINGFORK,Main            ,8927.3
696.9298
River Rch & RM=SPRINGFORK,Main            ,8601.9
984.2244
River Rch & RM=SPRINGFORK,Main            ,7648.8
 1002.37
River Rch & RM=SPRINGFORK,Main            ,4616.8
1108.674
River Rch & RM=SPRINGFORK,Main            ,888.5
1225.179
River Rch & RM=SPRINGFORK,Main            ,602.5
1382.805
Boundary for River Rch & Prof#=SPRINGFORK,Main            , 1
Up Type= 0
Dn Type= 3
Dn Slope=0.013
DSS Import GetInterval= 0
DSS Import GetPeak= 0
DSS Import FillOption= 0

--- SPRINGFORK.g01 (geometry) ---

Geom Title=USGS 10m DEM
Program Version=4.10

River Reach=SPRINGFORK      ,Main
Reach XY= 30
     1819016.211      472407.076     1819028.426      472620.748
      1819073.59      472723.938     1818883.201      472965.142
     1818796.222      473133.371     1818564.104       473318.44
     1818316.653      473744.139        1818242.      473780.597
      1818114.69      473793.543     1817480.551      474508.559
     1816807.854      475044.135     1816557.972      475325.736
     1816490.264      475426.431     1816434.243      475603.162
     1816241.187      475871.912     1816123.826      476248.996
     1816120.472      476492.403     1816151.604      476827.468
     1816293.097      477179.204     1816284.069      477327.815
     1816231.583      477551.431     1816156.986      477723.649
     1815934.069      478018.093      1815872.11      478420.658
     1815762.731      478498.142     1815582.735      478553.916
     1815008.947      478653.142     1814952.355      478701.089
     1814842.468      478903.768     1814593.053      479140.403

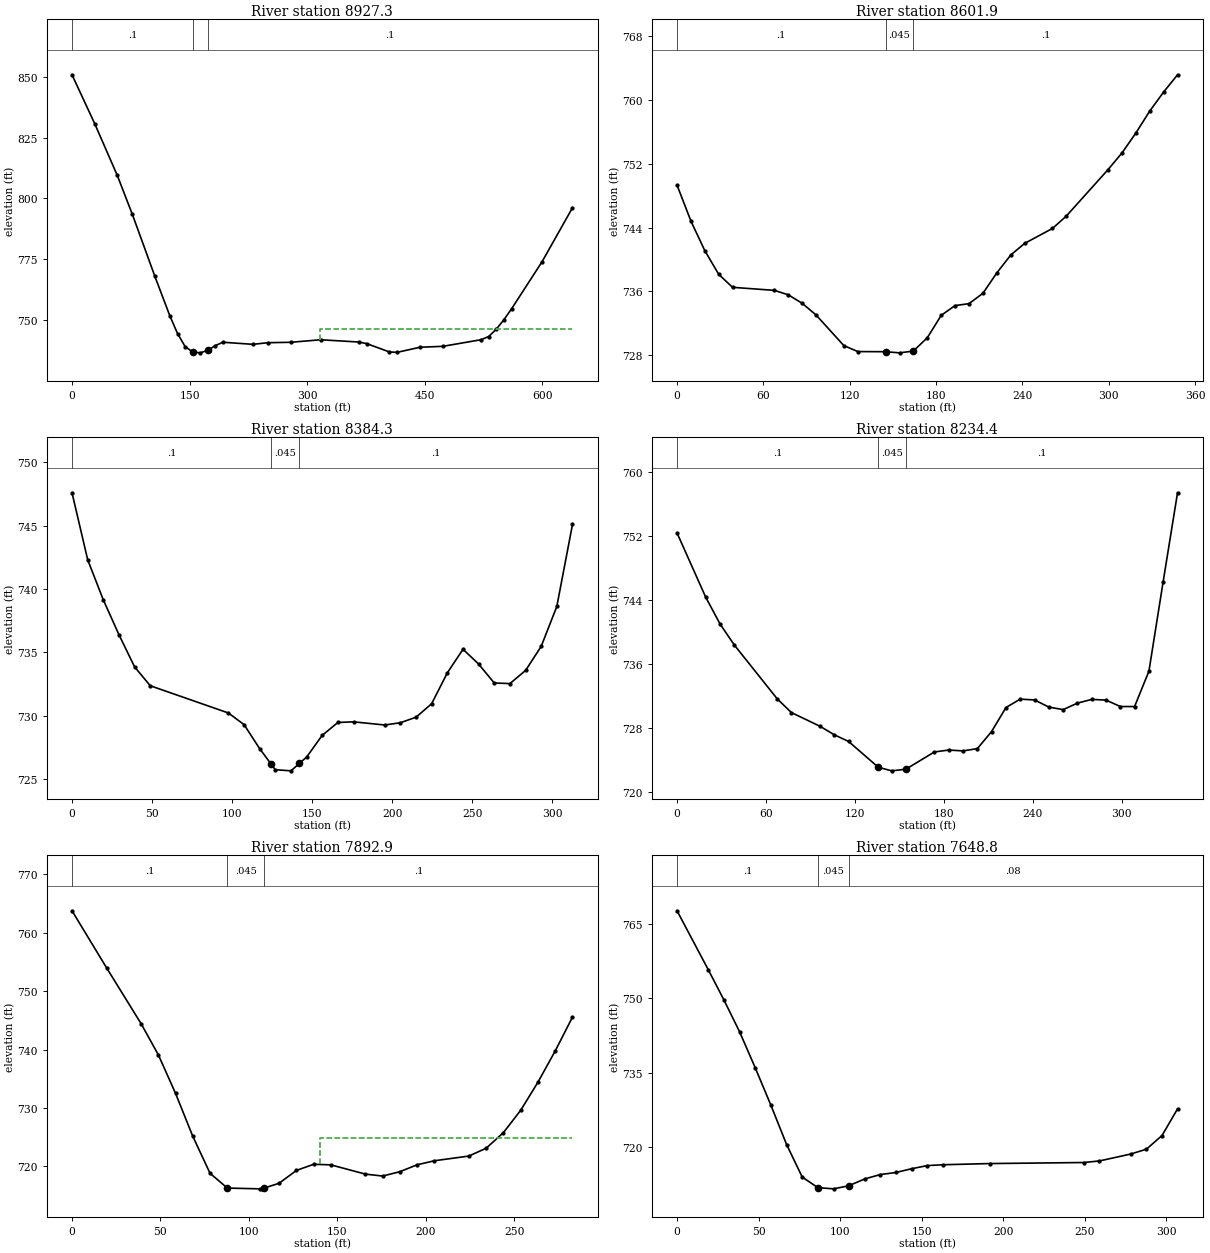
Type RM Length L Ch R = 1 ,8927.3  ,312.2,325.4,336.1
XS GIS Cut Line= 3
     1818849.171      472428.537     1819166.484      472437.319
     1819431.106      472619.393
#Sta/Elev= 30
       0  850.83    28.9  830.78    57.7  809.49      77  793.43   105.8  767.87
     125  751.54   134.7  744.37   144.3  739.06   153.9  736.85   163.5  736.46
   173.2737.4804   182.8  739.42   192.4  740.82   230.9  739.96   250.1  740.63
     279   740.8   317.4  741.84   366.1   740.9   375.8  740.28     405  736.83
   414.8  736.66     444  738.76   473.2  739.14   521.8  741.85   531.6  743.16
   541.3  746.17     551  750.04   560.8  754.54   599.7   773.9   638.6  796.14
#Mann= 3 , 0 , 0
       0      .1       0   153.9    .045       0   173.2      .1       0
#XS Ineff= 2 , 0
                          316.96          746.42
Permanent Ineff=
       F       F
Bank Sta=153.9,173.2
XS Rating Curve= 0 ,0
Exp/Cntr=0.3,0.1

Type RM Length L Ch R = 1 ,8601.9  ,217.2,217.6,217.3
XS GIS Cut Line= 2
     1818925.082      472661.998     1819226.471      472835.609
#Sta/Elev= 30
       0  749.33     9.7   744.8    19.3  741.11      29  738.13    38.6  736.51
    67.6  736.13    77.3  735.57      87   734.5    96.6  733.04   115.9   729.2
   125.6  728.45   144.9  728.43   154.6  728.29   164.2  728.51   173.9  730.18
   183.6     733   193.2  734.22   202.9  734.46   212.6  735.77   222.2  738.32
   231.9  740.56   241.5  742.02   260.9   743.9   270.5  745.45   299.5  751.28
   309.2  753.37   318.8  755.86   328.5  758.63   338.2  761.03   347.8  763.18
#Mann= 3 , 0 , 0
       0      .1       0   144.9    .045       0   164.2      .1       0
Bank Sta=144.9,164.2
XS Rating Curve= 0 ,0
Exp/Cntr=0.3,0.1

Type RM Length L Ch R = 1 ,8384.3  ,147.7,149.9,151.1
XS GIS Cut Line= 2
     1818812.793      472841.572     1819083.627      472997.822
#Sta/Elev= 30
       0   747.6     9.8  742.31    19.5  739.16    29.3   736.4    39.1  733.85
    48.9  732.36    97.7  730.21   107.5  729.29   117.2   727.4  124.31726.1884
     127  725.73   136.8  725.64     142  726.22   146.6  726.73   156.3  728.44
   166.1  729.46   175.9  729.51   195.4  729.26   205.2  729.44     215  729.88
   224.7  730.94   234.5  733.38   244.3  735.24     254  734.08   263.8  732.58
   273.6  732.53   283.4  733.57   293.1  735.46   302.9  738.62   312.7   745.1
#Mann= 3 , 0 , 0
       0      .1       0  124.31    .045       0     142      .1       0
Bank Sta=124.31,142
XS Rating Curve= 0 ,0
Exp/Cntr=0.3,0.1

Type RM Length L Ch R = 1 ,8234.4  ,338.7,341.5,344.5
XS GIS Cut Line= 2
     1818739.877      472957.892     1819021.995      473143.656
#Sta/Elev= 30
       0  752.39    19.3  744.38      29  741.02    38.6   738.4    67.6  731.66
    77.2  729.94    96.5  728.23   106.2  727.16   115.8  726.33   135.8  723.11
   144.8  722.66   154.4  722.86   173.7  725.02   183.4  725.26     193  725.15
   202.7  725.44   212.3  727.57     222  730.57   231.6  731.62   241.3  731.52
   250.9  730.63   260.6  730.31   270.2  731.12   279.9  731.59   289.5   731.5
   299.2   730.7   308.8  730.69   318.5  735.12   328.1  746.31   337.8  757.41
#Mann= 3 , 0 , 0
       0      .1       0   135.8    .045       0   154.4      .1       0
Bank Sta=135.8,154.4
XS Rating Curve= 0 ,0
Exp/Cntr=0.3,0.1

Type RM Length L Ch R = 1 ,7892.9  ,247.9,244.1,240.2
XS GIS Cut Line= 2
     1818543.339       473201.42     1818753.849       473390.19
#Sta/Elev= 27
       0  763.76    19.5  754.01      39  744.45    48.8  739.09    58.5   732.5
    68.2  725.18      78  718.81    87.8  716.28   106.2  716.15   107.2  716.15
   108.7716.2955     117   717.1   126.8   719.3   136.5  720.35   146.2  720.26
   165.8  718.67   175.5  718.34   185.2  719.08     195  720.27   204.8  720.96
   224.2  721.76     234   723.1   243.8  725.79   253.5  729.59   263.2  734.37
     273  739.74   282.8  745.56
#Mann= 3 , 0 , 0
       0      .1       0    87.8    .045       0   108.7      .1       0
#XS Ineff= 2 , 0
                          139.91          724.85
Permanent Ineff=
       F       F
Bank Sta=87.8,108.7
XS Rating Curve= 0 ,0
Exp/Cntr=0.3,0.1

Type RM Length L Ch R = 1 ,7648.8  ,279.9,281.5,283.1
XS GIS Cut Line= 2
     1818397.399      473413.859     1818656.948      473577.922
#Sta/Elev= 24
       0  767.66    19.2  755.74    28.8  749.64    38.4  743.22      48  735.95
    57.6  728.41    67.2   720.5    76.8  713.93    86.4   711.8      96  711.56
   105.3  712.18   115.2  713.57   124.7  714.44   134.3  714.86   143.9  715.62
   153.5  716.25   163.1  716.42   191.9  716.66   249.5  716.87   259.1  717.19
   278.3  718.58   287.9  719.56   297.5  722.32     307  727.69
#Mann= 3 , 0 , 0
       0      .1       0    86.4    .045       0   105.3     .08       0
Bank Sta=86.4,105.3
XS Rating Curve= 0 ,0
Exp/Cntr=0.3,0.1

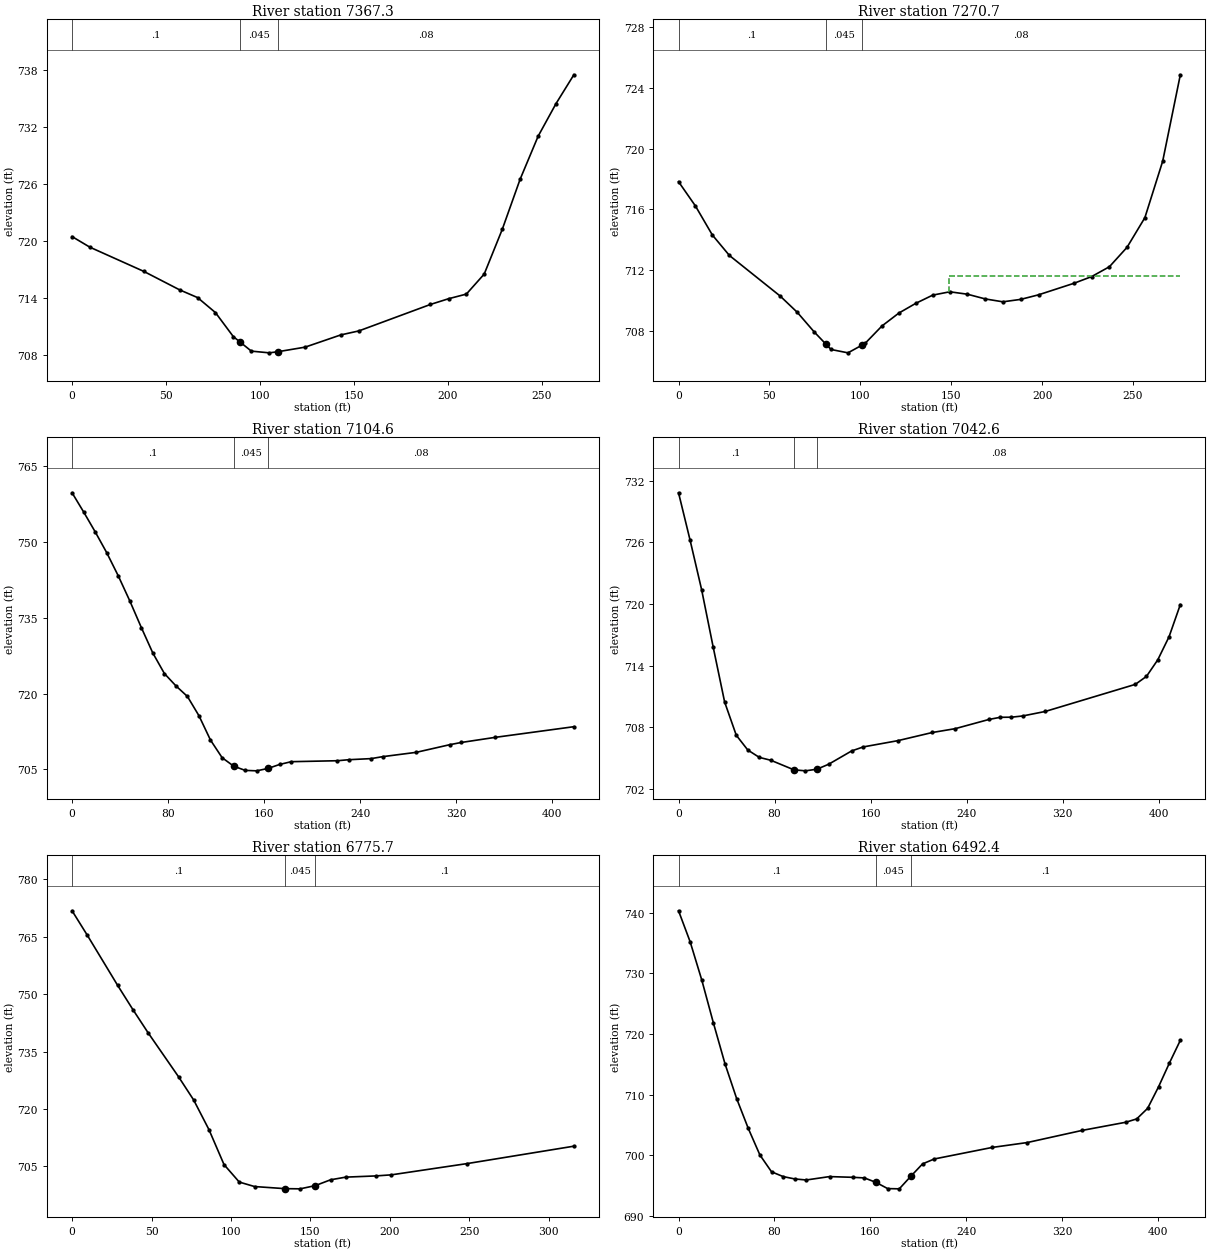
Type RM Length L Ch R = 1 ,7367.3  ,83.5,96.6,109.8
XS GIS Cut Line= 2
     1818264.568      473649.388     1818479.845      473807.374
#Sta/Elev= 23
       0  720.45     9.5  719.33    38.2  716.78    57.2  714.84    66.8  714.02
    76.3  712.44    85.8  709.91    89.4709.3375    95.4  708.38   104.9   708.2
   109.4708.3133     124   708.8     143  710.09   152.6  710.51   190.7   713.3
   200.3   713.9   209.8  714.39   219.3   716.5   228.9  721.21   238.4  726.49
     248  731.03   257.5  734.46     267   737.5
#Mann= 3 , 0 , 0
       0      .1       0    89.4    .045       0   109.4     .08       0
Bank Sta=89.4,109.4
XS Rating Curve= 0 ,0
Exp/Cntr=0.3,0.1

Type RM Length L Ch R = 1 ,7270.7  ,197.6,166.1,93
XS GIS Cut Line= 3
     1818238.678      473681.487     1818291.364       473821.05
     1818390.572       473900.08
#Sta/Elev= 29
       0  717.83     9.3  716.23    18.6  714.32      28  712.97    55.9   710.3
    65.3  709.23    74.6  707.94    80.9707.1525    83.9  706.78    93.2  706.56
   100.9707.0667   102.6  707.18   111.9  708.33   121.2  709.18   130.5  709.82
   139.8  710.36   149.2  710.58   158.9  710.42   168.7  710.11   178.4  709.92
   188.2  710.08     198  710.38   217.5  711.14   227.2  711.58     237  712.23
   246.7  713.51   256.5  715.46   266.3  719.18     276  724.87
#Mann= 3 , 0 , 0
       0      .1       0    80.9    .045       0   100.9     .08       0
#XS Ineff= 2 , 0
                           148.9          711.62
Permanent Ineff=
       F       F
Bank Sta=80.9,100.9
XS Rating Curve= 0 ,0
Exp/Cntr=0.3,0.1

Type RM Length L Ch R = 1 ,7104.6  ,65.7,62,98.7
XS GIS Cut Line= 3
     1817959.201      473811.588     1818179.264      473790.526
     1818323.435      473924.656
#Sta/Elev= 29
       0  759.73     9.6  755.95    19.2  752.03    28.8  747.91    38.4  743.34
    48.1  738.34    57.7  733.07    67.3  728.02    76.9  723.98    86.5  721.54
    96.1  719.44   105.7  715.63   115.3  710.82     125  707.33   134.6  705.66
   144.2  704.82   153.8  704.73   163.4  705.22     173     706   182.6  706.54
   221.1  706.73   230.4  706.93   249.2  707.15   258.6  707.53   286.7  708.39
   314.8  709.91   324.2  710.34   352.4  711.35     418  713.46
#Mann= 3 , 0 , 0
       0      .1       0   134.6    .045       0   163.4     .08       0
Bank Sta=134.6,163.4
XS Rating Curve= 0 ,0
Exp/Cntr=0.3,0.1

Type RM Length L Ch R = 1 ,7042.6  ,239.8,266.9,295.3
XS GIS Cut Line= 3
      1817967.19       473858.07     1818187.253      473837.008
     1818331.424      473971.138
#Sta/Elev= 28
       0  730.84     9.6  726.23    19.2  721.41    28.8  715.83    38.4  710.44
    48.1   707.2    57.7  705.76    67.3  705.04    76.9  704.76    96.1  703.83
   105.7  703.73   115.3  703.89     125  704.37   144.2  705.67   153.8  706.06
   182.6  706.67   211.5  707.47   230.4  707.84   258.6  708.74     268  708.95
   277.3  708.96   286.7  709.08   305.5  709.52   380.5  712.16   389.8  712.94
   399.2  714.55   408.6   716.8     418  719.94
#Mann= 3 , 0 , 0
       0      .1       0    96.1    .045       0   115.3     .08       0
Bank Sta=96.1,115.3
XS Rating Curve= 0 ,0
Exp/Cntr=0.3,0.1

Type RM Length L Ch R = 1 ,6775.7  ,284.3,283.2,282
XS GIS Cut Line= 2
     1817801.433      473930.943     1818005.426      474171.828
#Sta/Elev= 20
       0  771.79     9.6  765.39    28.7  752.27    38.3  745.94    47.8  739.92
      67  728.39    76.5  722.33    86.1   714.6    95.6  705.44   105.2  700.87
   114.8   699.7   133.9  699.15   143.5   699.1     153  699.94   162.6  701.46
   172.2  702.16   191.3  702.48   200.9  702.76   248.7  705.71   315.7  710.25
#Mann= 3 , 0 , 0
       0      .1       0   133.9    .045       0     153      .1       0
Bank Sta=133.9,153
XS Rating Curve= 0 ,0
Exp/Cntr=0.3,0.1

Type RM Length L Ch R = 1 ,6492.4  ,308,308.1,308.2
XS GIS Cut Line= 3
     1817594.606      474129.782     1817799.991       474349.22
     1817858.364      474451.913
#Sta/Elev= 30
       0  740.31     9.7  735.19    19.4  728.89    29.1  721.81    38.8  715.06
    48.5  709.34    58.2  704.42    67.9  700.04    77.6  697.27    87.3  696.48
      97  696.09   106.6  695.92     126  696.48   145.4  696.36   155.1  696.26
   164.8  695.52   174.5   694.5   184.2  694.46   193.7 696.507   203.6  698.57
   213.3  699.38   261.8  701.29   290.9  702.09   336.9   704.1   373.2  705.44
   382.3  705.99   391.4  707.73   400.5  711.27   409.6  715.21   418.7  718.95
#Mann= 3 , 0 , 0
       0      .1       0   164.8    .045       0   193.7      .1       0
Bank Sta=164.8,193.7
XS Rating Curve= 0 ,0
Exp/Cntr=0.3,0.1

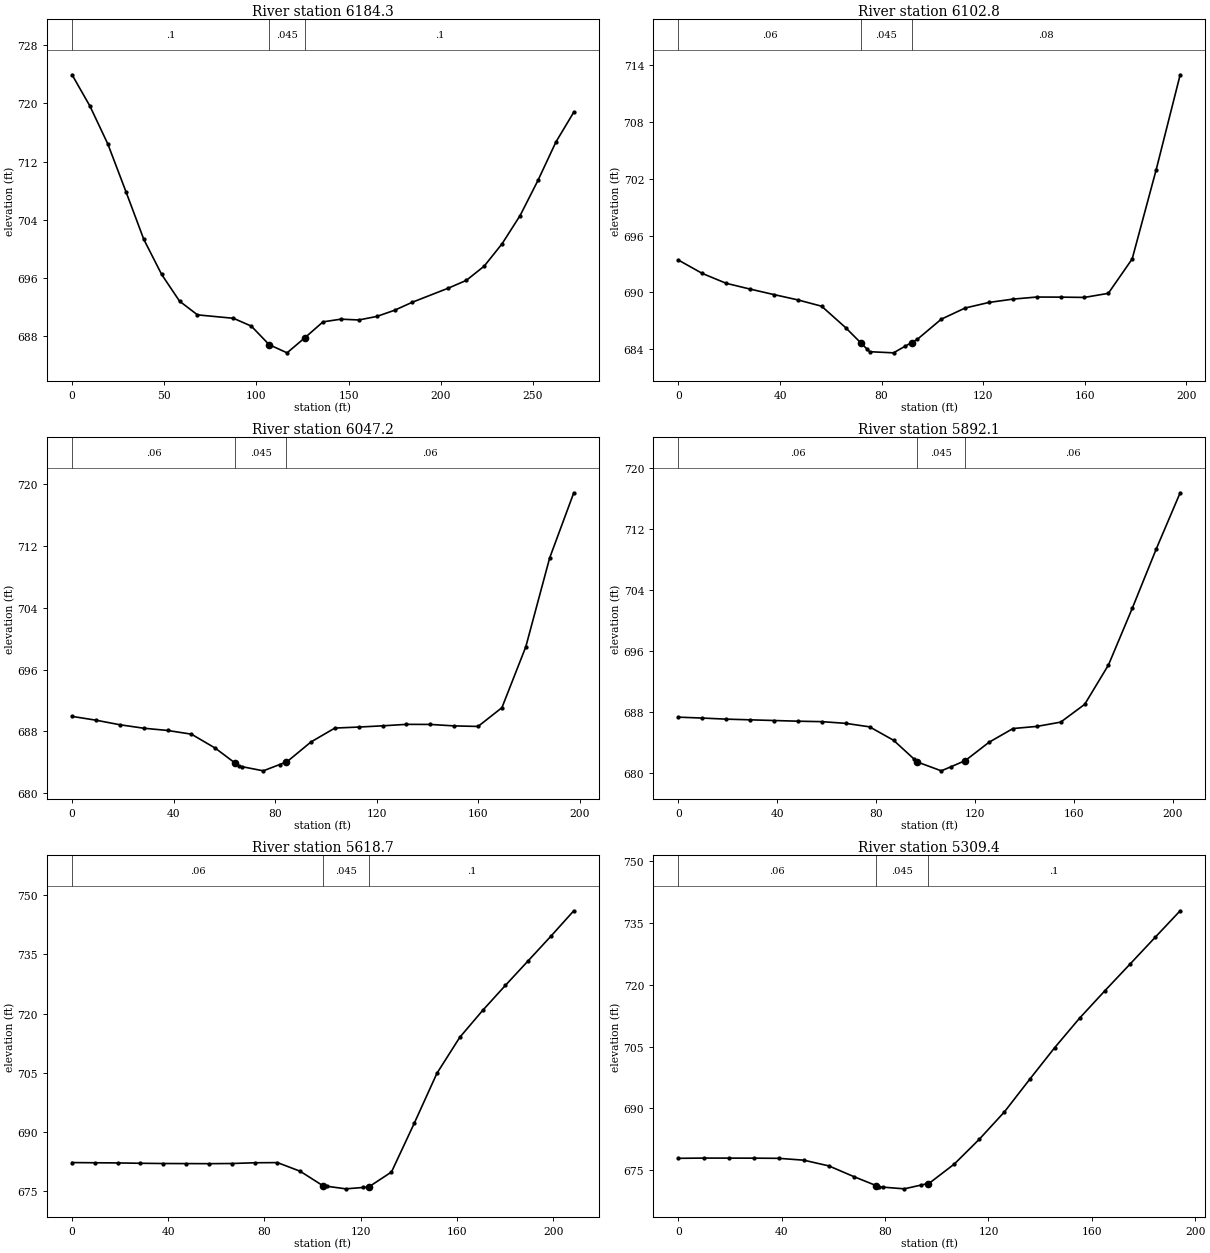
Type RM Length L Ch R = 1 ,6184.3  ,79,81.5,83.8
XS GIS Cut Line= 2
     1817423.572      474395.973     1817608.468      474595.626
#Sta/Elev= 27
       0   723.9     9.7   719.6    19.4   714.4    29.2  707.88    38.9  701.32
    48.6   696.5    58.3  692.84      68  690.96    87.5  690.49    97.2  689.42
   106.9  686.87   116.6  685.75   126.3  687.83   136.1     690   145.8  690.37
   155.5  690.26   165.2  690.74   174.9  691.59   184.6   692.7   204.1  694.63
   213.8  695.69   223.5  697.64   233.2  700.71     243  704.59   252.7  709.42
   262.4  714.67   272.1  718.77
#Mann= 3 , 0 , 0
       0      .1       0   106.9    .045       0   126.3      .1       0
Bank Sta=106.9,126.3
XS Rating Curve= 0 ,0
Exp/Cntr=0.3,0.1

Type RM Length L Ch R = 1 ,6102.8  ,55.7,55.6,55.7
XS GIS Cut Line= 2
     1817396.321      474473.438     1817514.287      474631.899
#Sta/Elev= 26
       0  693.41     9.4     692    18.8  690.96    28.2  690.35    37.6  689.77
      47  689.21    56.4  688.54    65.8  686.29    71.8684.6806    74.3  684.01
    75.3  683.74    84.7  683.62    89.3  684.32    91.8684.7002    94.1  685.05
   103.5  687.17   112.9  688.35   122.3  688.94   131.7  689.29   141.1  689.51
   150.5   689.5   159.9  689.47   169.3   689.9   178.7  693.53   188.1  702.89
   197.6  712.97
#Mann= 3 , 0 , 0
       0     .06       0    71.8    .045       0    91.8     .08       0
Bank Sta=71.8,91.8
XS Rating Curve= 0 ,0
Exp/Cntr=0.3,0.1

Type RM Length L Ch R = 1 ,6047.2  ,157,155.1,153.2
XS GIS Cut Line= 2
     1817355.826      474512.173     1817473.791      474670.634
#Sta/Elev= 26
       0  689.93     9.4  689.44    18.8  688.85    28.2   688.4    37.6  688.11
      47  687.63    56.4  685.82    64.3683.8618    65.8  683.49    66.8  683.43
    75.3  682.88    81.8   683.7    84.3 684.019    84.7  684.07    94.1  686.62
   103.5  688.42   112.9  688.55   122.3  688.71   131.7   688.9   141.1  688.89
   150.5   688.7   159.9  688.63   169.3  691.06   178.7  698.94   188.1  710.45
   197.6  718.89
#Mann= 3 , 0 , 0
       0     .06       0    64.3    .045       0    84.3     .06       0
Bank Sta=64.3,84.3
XS Rating Curve= 0 ,0
Exp/Cntr=0.3,0.1

Type RM Length L Ch R = 1 ,5892.1  ,271.6,273.4,275.2
XS GIS Cut Line= 2
      1817205.69      474584.341     1817340.238      474736.251
#Sta/Elev= 24
       0  687.35     9.7  687.23    19.3  687.09      29     687    38.6  686.91
    48.3  686.82      58  686.76    67.6  686.54    77.3  686.08      87  684.32
    95.1  681.92    96.6  681.48   106.3  680.32   110.1  680.84     116  681.66
   125.6  684.06   135.3  685.86     145  686.14   154.6   686.7   164.3  689.03
   173.9  694.18   183.6  701.66   193.3  709.43   202.9  716.73
#Mann= 3 , 0 , 0
       0     .06       0    96.6    .045       0     116     .06       0
Bank Sta=96.6,116
XS Rating Curve= 0 ,0
Exp/Cntr=0.3,0.1

Type RM Length L Ch R = 1 ,5618.7  ,310.4,309.3,308.1
XS GIS Cut Line= 2
     1817005.408      474756.167     1817130.798      474922.932
#Sta/Elev= 26
       0  682.22     9.5  682.17      19  682.13    28.4  682.04    37.9  681.98
    47.4  681.96    56.9  681.94    66.4  681.98    75.9  682.17    85.4  682.21
    94.8  680.03   104.3  676.35   105.9  676.22   113.8  675.56   120.9   675.9
   123.3  676.02   123.4  676.06   132.8  679.82   142.3  692.22   151.7  704.85
   161.2  713.97   170.7  720.78   180.2  727.16   189.7  733.41   199.2  739.68
   208.6  746.05
#Mann= 3 , 0 , 0
       0     .06       0   104.3    .045       0   123.4      .1       0
Bank Sta=104.3,123.4
XS Rating Curve= 0 ,0
Exp/Cntr=0.3,0.1

Type RM Length L Ch R = 1 ,5309.4  ,264.2,262.4,260.4
XS GIS Cut Line= 2
     1816769.364      474960.577     1816893.496      475109.883
#Sta/Elev= 25
       0  677.86     9.7  677.92    19.4  677.91    29.1   677.9    38.8  677.86
    48.5  677.41    58.2  676.02      68  673.39    76.5671.2431    77.7  670.94
      79  670.87    87.4  670.45      94  671.38    96.5671.7349    97.1  671.82
   106.8  676.48   116.5  682.52   126.2  689.15   135.9     697   145.6   704.7
   155.3  711.91     165   718.5   174.8  725.02   184.5   731.5   194.2  737.96
#Mann= 3 , 0 , 0
       0     .06       0    76.5    .045       0    96.5      .1       0
Bank Sta=76.5,96.5
XS Rating Curve= 0 ,0
Exp/Cntr=0.3,0.1

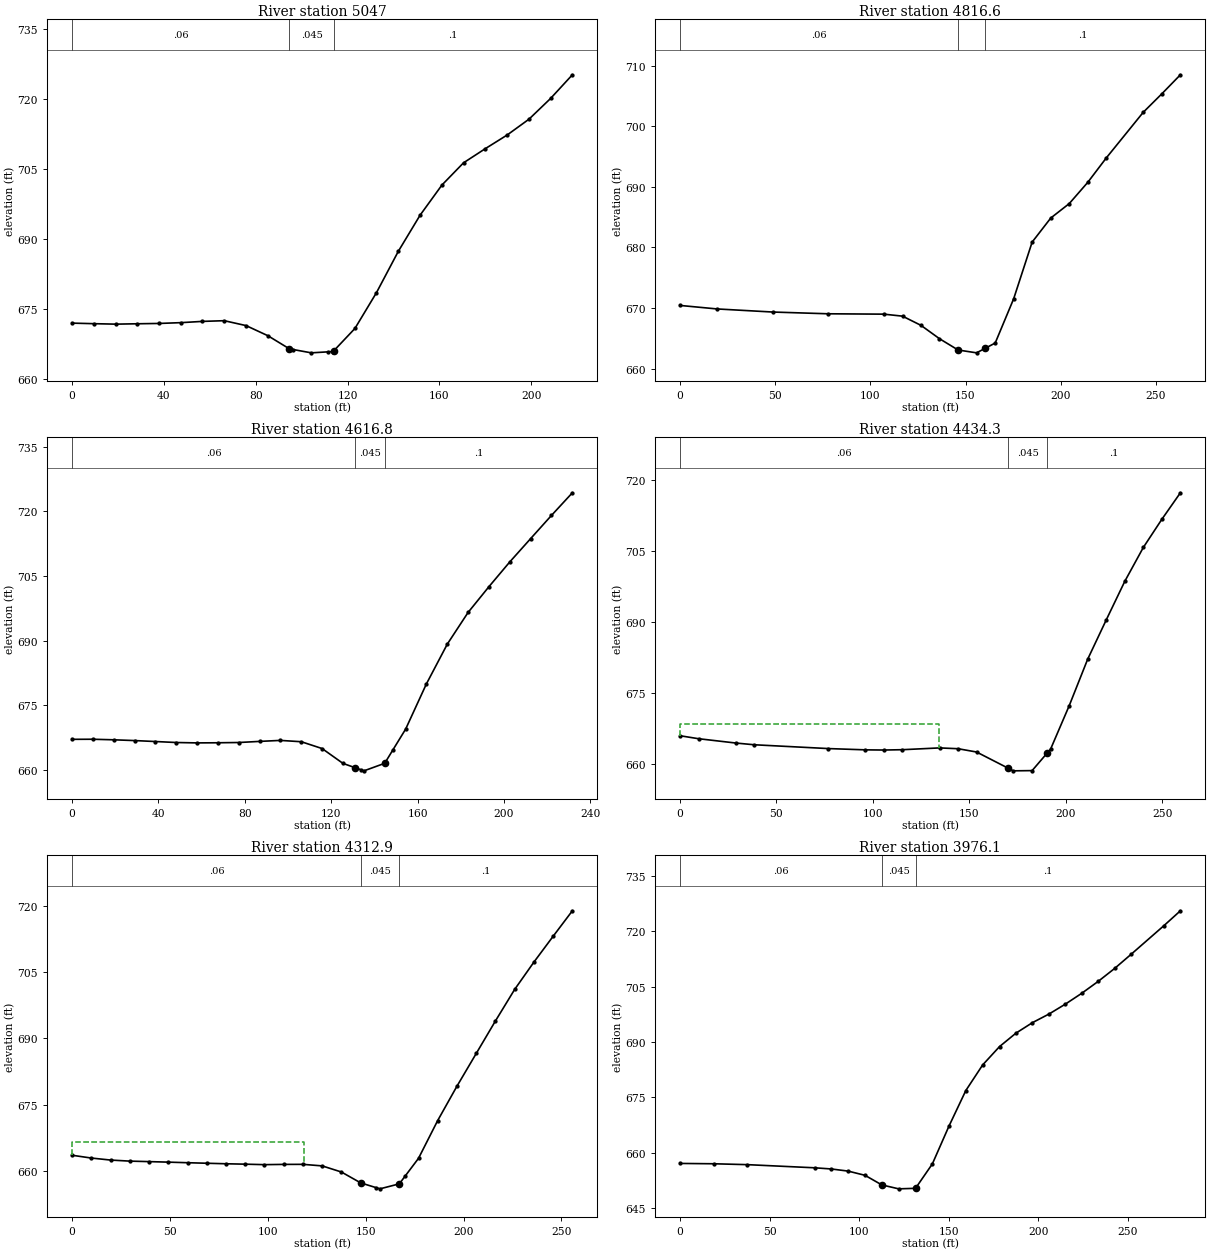
Type RM Length L Ch R = 1 ,5047    ,235,230.4,225.7
XS GIS Cut Line= 2
      1816574.25      475146.025     1816727.028      475301.407
#Sta/Elev= 27
       0  672.04     9.5  671.92      19  671.82    28.4   671.9    37.9  671.97
    47.4  672.14    56.8  672.41    66.3  672.56    75.8  671.51    85.3  669.34
    94.7  666.52    96.4  666.37   104.2  665.67   111.4  665.88   113.7  665.95
   113.9 666.054   123.2  670.89   132.6  678.58   142.1  687.43   151.6  695.19
   161.1  701.64   170.5   706.4     180  709.44   189.5  712.36     199  715.75
   208.4  720.19   217.9  725.27
#Mann= 3 , 0 , 0
       0     .06       0    94.7    .045       0   113.9      .1       0
Bank Sta=94.7,113.9
XS Rating Curve= 0 ,0
Exp/Cntr=0.3,0.1

Type RM Length L Ch R = 1 ,4816.6  ,202,199.9,197.8
XS GIS Cut Line= 2
     1816381.447      475319.015     1816600.383      475464.608
#Sta/Elev= 21
       0  670.42    19.5  669.84    48.7  669.33    77.9  669.04   107.1  668.98
   116.9  668.65   126.6  667.13   136.3  664.93   146.1  663.06   155.8  662.59
   160.2663.3146   165.6  664.21   175.3  671.52     185  680.88   194.8  684.86
   204.5  687.24   214.2  690.74     224   694.8   243.4  702.33   253.2  705.39
   262.9  708.52
#Mann= 3 , 0 , 0
       0     .06       0   146.1    .045       0   160.2      .1       0
Bank Sta=146.1,160.2
XS Rating Curve= 0 ,0
Exp/Cntr=0.3,0.1

Type RM Length L Ch R = 1 ,4616.8  ,179.7,182.4,185.1
XS GIS Cut Line= 2
      1816316.79      475521.919     1816520.916      475631.552
#Sta/Elev= 28
       0  667.06     9.6  667.08    19.3  666.95      29  666.77    38.6  666.55
    48.3  666.32    57.9  666.23    67.6  666.26    77.2  666.32    86.9  666.58
    96.5  666.81   106.2   666.5   115.8  664.92   125.5  661.46   131.2660.4521
   133.7  660.01   135.2  659.74   144.8  661.49   148.7  664.69   154.5  669.44
   164.1  679.93   173.8  689.19   183.4  696.53   193.1  702.54   202.7  708.26
   212.4   713.7     222  719.06   231.7  724.33
#Mann= 3 , 0 , 0
       0     .06       0   131.2    .045       0   144.8      .1       0
Bank Sta=131.2,144.8
XS Rating Curve= 0 ,0
Exp/Cntr=0.3,0.1

Type RM Length L Ch R = 1 ,4434.3  ,124.1,121.5,118.8
XS GIS Cut Line= 2
     1816184.186       475630.79     1816396.686      475779.748
#Sta/Elev= 23
       0  665.89     9.6  665.26    28.8  664.35    38.4  663.98    76.9  663.17
    96.1   662.9   105.7  662.86   115.3  662.93   134.6  663.31   144.2  663.14
   153.8  662.44   170.3658.9846   172.8  658.45   182.6   658.5   190.3662.1675
   192.2  663.07   201.8  672.22   211.4   682.1   221.1  690.49   230.7  698.65
   240.3  705.82   249.9  711.78   259.5  717.39
#Mann= 3 , 0 , 0
       0     .06       0   170.3    .045       0   190.3      .1       0
#XS Ineff= 2 , 0
          134.14  668.29
Permanent Ineff=
       F       F
Bank Sta=170.3,190.3
XS Rating Curve= 0 ,0
Exp/Cntr=0.3,0.1

Type RM Length L Ch R = 1 ,4312.9  ,340.6,336.8,332.7
XS GIS Cut Line= 2
     1816121.686      475758.394     1816346.686      475879.748
#Sta/Elev= 29
       0  663.55     9.8  662.92    19.7  662.46    29.5  662.22    39.3  662.11
    49.2  661.99      59  661.86    68.8  661.74    78.7  661.62    88.5  661.53
    98.3  661.42   108.2  661.48     118  661.49   127.8  661.14   137.6  659.76
   147.5  657.29   155.2  656.24   157.3  655.95   167.2  657.08   170.2  658.85
     177  662.85   186.8   671.4   196.6  679.14   206.5  686.58   216.3  693.93
   226.1  701.05     236  707.27   245.8   713.1   255.6  718.85
#Mann= 3 , 0 , 0
       0     .06       0   147.5    .045       0   167.2      .1       0
#XS Ineff= 2 , 0
          118.54  666.45
Permanent Ineff=
       F       F
Bank Sta=147.5,167.2
XS Rating Curve= 0 ,0
Exp/Cntr=0.3,0.1

Type RM Length L Ch R = 1 ,3976.1  ,198.9,192,184.7
XS GIS Cut Line= 3
     1816033.361      476111.606     1816202.632       476168.03
     1816303.543      476165.859
#Sta/Elev= 25
       0  657.11    18.8  657.02    37.6  656.78    75.1  655.93    84.5  655.61
    93.9  655.03   103.3  653.89   112.7  651.29   122.1  650.23   131.5  650.37
   140.9  656.98   150.2  667.24   159.6  676.86     169  683.79   178.4  688.75
   187.6   692.4   196.8  695.24     206  697.56   215.1  700.23   224.3  703.18
   233.5  706.41   242.7  709.92   251.8  713.71   270.2   721.5   279.4  725.53
#Mann= 3 , 0 , 0
       0     .06       0   112.7    .045       0   131.5      .1       0
Bank Sta=112.7,131.5
XS Rating Curve= 0 ,0
Exp/Cntr=0.3,0.1

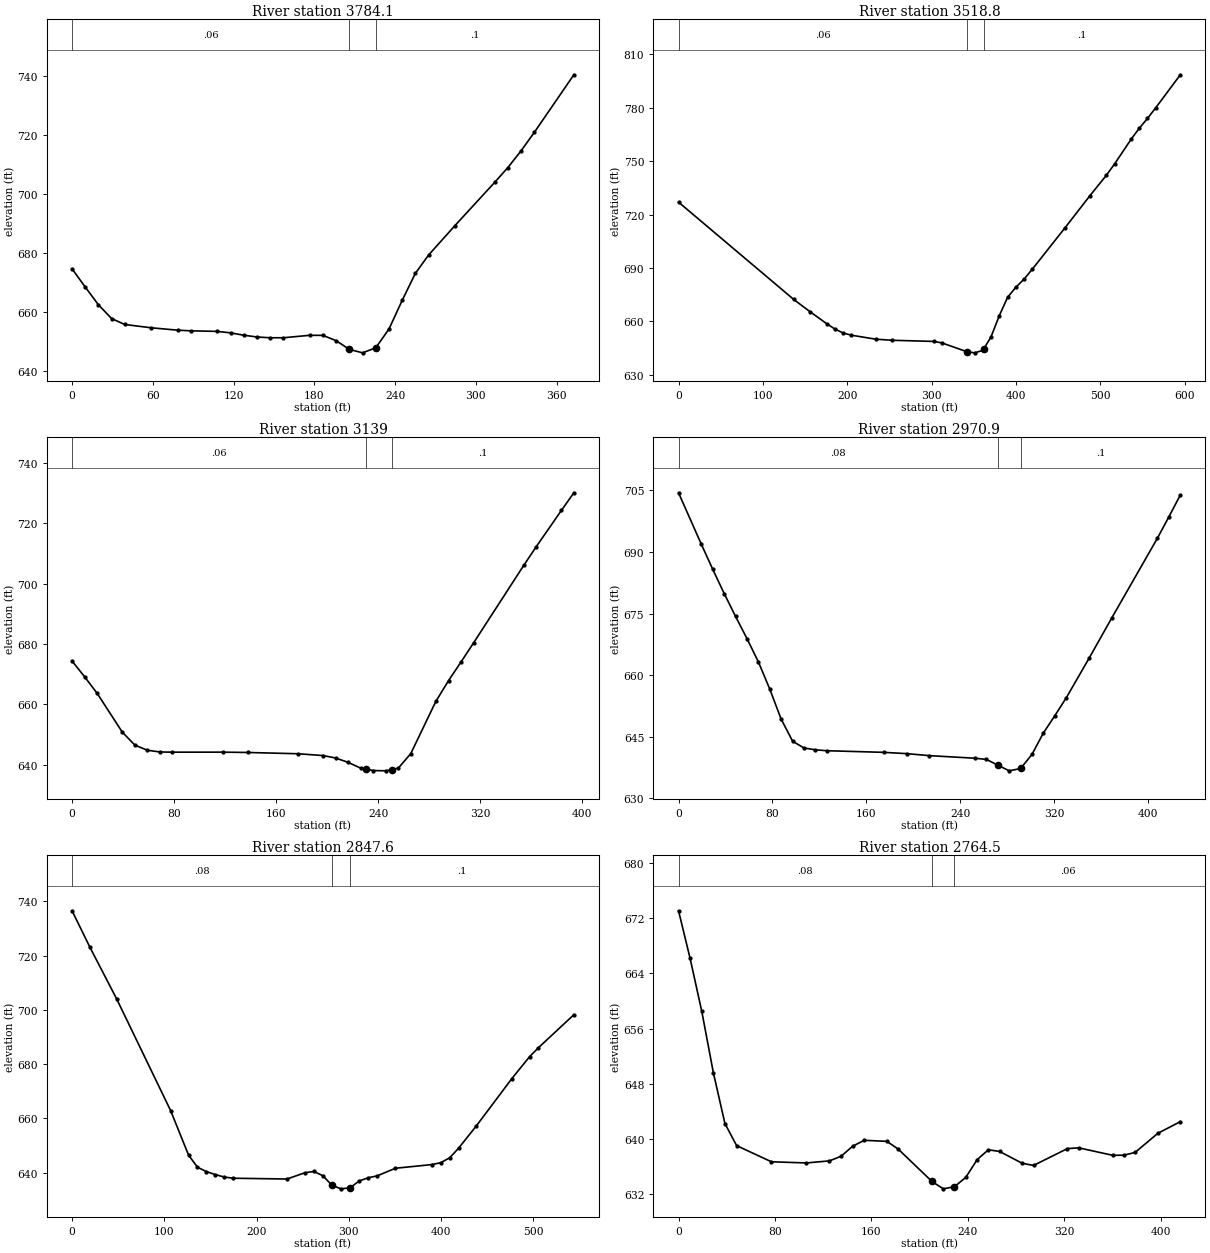
Type RM Length L Ch R = 1 ,3784.1  ,266.2,265.3,264.4
XS GIS Cut Line= 2
      1815899.61      476337.113     1816272.501       476339.41
#Sta/Elev= 30
       0  674.61     9.8  668.42    19.6  662.41    29.4  657.72    39.2  655.72
    58.9   654.6    78.5  653.79    88.3  653.57   107.9  653.38   117.8  652.88
   127.6  652.08   137.4  651.48   147.2  651.22     157  651.22   176.6  652.05
   186.4  652.03   196.3  650.21   206.1  647.27   215.9   646.1   225.7  647.83
   235.5  654.17   245.3  663.89   255.1  673.08     265  679.33   284.6  689.32
     314  703.94   323.8  708.95   333.6  714.63   343.5  720.92   372.9  740.48
#Mann= 3 , 0 , 0
       0     .06       0   206.1    .045       0   225.7      .1       0
Bank Sta=206.1,225.7
XS Rating Curve= 0 ,0
Exp/Cntr=0.3,0.1

Type RM Length L Ch R = 1 ,3518.8  ,387,379.8,372.5
XS GIS Cut Line= 2
     1815772.981      476615.508     1816367.458      476595.322
#Sta/Elev= 30
       0     727   136.5  672.32     156  665.37   175.5  658.73   185.3  655.69
     195  653.48   204.8  652.22     234  649.96   253.5  649.36   302.3  648.72
     312  647.91   341.6642.9686     351   642.3   360.8  643.72   361.6644.3509
   370.5  651.37   380.3  663.27     390  673.46   399.8  679.16   409.6  683.71
   419.3  689.29   458.3  712.68   487.6  730.59   507.1  742.09   516.8  748.42
   536.3  762.23   546.1   768.5   555.8  774.01   565.6  780.01   594.8  798.58
#Mann= 3 , 0 , 0
       0     .06       0   341.6    .045       0   361.6      .1       0
Bank Sta=341.6,361.6
XS Rating Curve= 0 ,0
Exp/Cntr=0.3,0.1

Type RM Length L Ch R = 1 ,3139    ,167.2,168.1,168.7
XS GIS Cut Line= 2
     1815978.644      477055.261     1816347.729      476918.706
#Sta/Elev= 29
       0  674.35     9.8  669.17    19.7  663.64    39.4  650.81    49.2  646.54
      59  644.82    68.9  644.25    78.7  644.18   118.1  644.19   137.7  644.08
   177.1  643.66   196.8  643.06   206.6  642.26   216.4  640.82   226.3   638.9
   230.5638.5615   236.1  638.11     246     638   250.5638.4012   255.8  638.87
   265.6   643.7   285.3  661.01   295.2  667.86     305  674.03   314.8  680.33
   354.2  706.03     364  712.22   383.7  724.21   393.5  730.07
#Mann= 3 , 0 , 0
       0     .06       0   230.5    .045       0   250.5      .1       0
Bank Sta=230.5,250.5
XS Rating Curve= 0 ,0
Exp/Cntr=0.3,0.1

Type RM Length L Ch R = 1 ,2970.9  ,117,123.2,129.7
XS GIS Cut Line= 2
     1816001.188      477215.005     1816406.989      477080.382
#Sta/Elev= 30
       0   704.4    19.4  691.88    29.2  685.74    38.9  679.87    48.6   674.3
    58.3  668.92      68  663.26    77.7  656.64    87.4  649.33    97.2  643.92
   106.9  642.27   116.6  641.83   126.3  641.61   174.9  641.21   194.3   640.9
   213.8  640.41   252.6  639.78   262.4  639.49   272.1  638.09   281.8  636.71
   291.5  637.28   301.2  640.72   310.9  645.93   320.7  650.15   330.4  654.49
   349.8   664.1   369.2  673.94   408.1  693.36   417.8  698.51   427.6  703.87
#Mann= 3 , 0 , 0
       0     .08       0   272.1    .045       0   291.5      .1       0
Bank Sta=272.1,291.5
XS Rating Curve= 0 ,0
Exp/Cntr=0.3,0.1

Type RM Length L Ch R = 1 ,2847.6  ,37.9,83.1,121.7
XS GIS Cut Line= 4
     1816008.541      477313.883     1816261.416      477245.279
      1816408.58      477239.332     1816527.441      477176.357
#Sta/Elev= 30
       0   736.5    19.4  723.02    48.5  703.91   106.8  662.88   126.2  646.51
   135.9  642.01   145.6   640.4   155.3  639.29     165  638.39   174.7  637.96
   232.9  637.67   252.3  639.97     262  640.45   271.8  638.89   281.6  635.37
   291.5  634.05   301.3  634.44   311.1  636.95   320.9  638.12   330.8  638.85
   350.4  641.63   389.7  642.98   399.5  643.68   409.3  645.51   418.9  649.03
   438.1  657.23   476.6  674.67   495.8  682.73   505.4  686.05   543.8   698.2
#Mann= 3 , 0 , 0
       0     .08       0   281.6    .045       0   301.3      .1       0
Bank Sta=281.6,301.3
XS Rating Curve= 0 ,0
Exp/Cntr=0.3,0.1

Type RM Length L Ch R = 1 ,2764.5  ,78.5,64,55.9
XS GIS Cut Line= 4
      1816118.03      477327.693     1816263.377      477276.364
     1816309.666       477388.92     1816443.502      477431.858
#Sta/Elev= 30
       0  673.08     9.6  666.18    19.3   658.5    28.9  649.62    38.5  642.26
    48.2  639.06    77.1  636.72     106  636.55   125.2  636.85   134.9  637.52
   144.5  638.98   154.1  639.83   172.9  639.68   182.2  638.57   210.3  633.87
   219.7   632.8     229  633.11   238.4  634.47   247.8  637.03   257.1  638.46
   266.5  638.21   285.2   636.5   294.6  636.19   322.7  638.63   332.1  638.74
   360.2  637.66   369.6  637.67   378.9  638.08   397.7  640.84   416.4  642.53
#Mann= 3 , 0 , 0
       0     .08       0   210.3    .045       0     229     .06       0
Bank Sta=210.3,229
XS Rating Curve= 0 ,0
Exp/Cntr=0.3,0.1

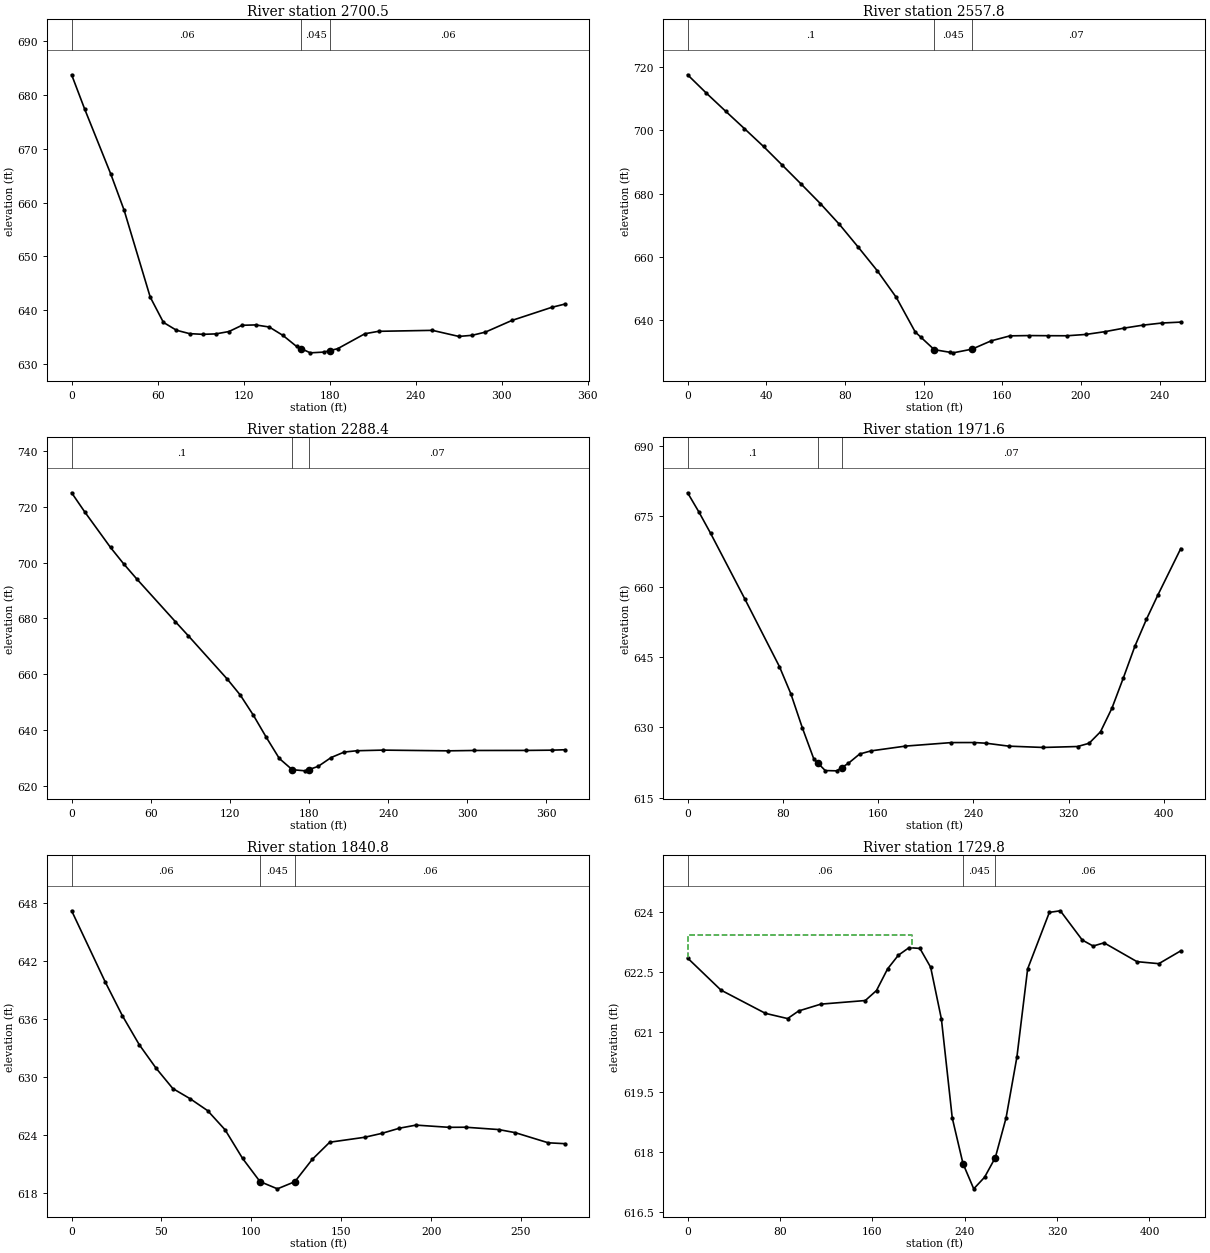
Type RM Length L Ch R = 1 ,2700.5  ,166,142.7,119.4
XS GIS Cut Line= 4
     1816131.185      477381.235     1816241.938      477338.246
     1816285.304      477443.981     1816385.924      477490.405
#Sta/Elev= 30
       0  683.76     9.1  677.38    27.4  665.24    36.6  658.59    54.8  642.44
      64  637.74    73.1  636.28    82.2  635.65    91.4  635.52   100.5   635.6
   109.7  636.04   118.8   637.2   128.3  637.27   137.8  636.88   147.4  635.31
   156.9  633.26   160.2632.8503   166.4  632.08   175.9  632.22   180.2632.5035
   185.5  632.85   204.5  635.63     214  636.08   251.6  636.26     270  635.13
   279.3  635.34   288.5  635.93     307   638.1   334.7  640.53   343.9  641.14
#Mann= 3 , 0 , 0
       0     .06       0   160.2    .045       0   180.2     .06       0
Bank Sta=160.2,180.2
XS Rating Curve= 0 ,0
Exp/Cntr=0.3,0.1

Type RM Length L Ch R = 1 ,2557.8  ,261.9,269.4,276.7
XS GIS Cut Line= 2
     1816115.843      477489.404     1816356.605      477559.393
#Sta/Elev= 29
       0  717.56     9.6  711.72    19.3  706.06    28.9  700.53    38.6  694.89
    48.2  688.94    57.9   682.9    67.5  676.83    77.2  670.24    86.8  663.02
    96.4  655.62   106.1  647.16   115.7  636.25   118.4  634.69   125.4  630.64
   133.4  629.81     135  629.64   144.6  630.81   154.3  633.43   163.9  635.01
   173.6   635.1   183.2  635.06   192.9  635.04   202.5  635.46   212.2  636.34
   221.8  637.45   231.4  638.39   241.1  639.07   250.7  639.36
#Mann= 3 , 0 , 0
       0      .1       0   125.4    .045       0   144.6     .07       0
Bank Sta=125.4,144.6
XS Rating Curve= 0 ,0
Exp/Cntr=0.3,0.1

Type RM Length L Ch R = 1 ,2288.4  ,319.1,316.9,314.4
XS GIS Cut Line= 2
     1815986.462      477670.396     1816292.885      477884.806
#Sta/Elev= 25
       0  725.03     9.8  718.26    29.5  705.42    39.4  699.59    49.2  694.24
    78.7  678.81    88.6  673.71   118.1   658.2   127.9  652.51   137.8  645.31
   147.6  637.38   157.5  629.78   167.3  625.76   177.2  625.35   179.7625.7607
     187  626.96   196.8  630.12   206.7  632.08   216.5  632.56   236.2  632.78
   285.4  632.52   305.1  632.65   344.5  632.67   364.2  632.76     374  632.91
#Mann= 3 , 0 , 0
       0      .1       0   167.3    .045       0   179.7     .07       0
Bank Sta=167.3,179.7
XS Rating Curve= 0 ,0
Exp/Cntr=0.3,0.1

Type RM Length L Ch R = 1 ,1971.6  ,140.8,130.8,120.4
XS GIS Cut Line= 2
     1815829.347      477960.745      1816191.83      478161.263
#Sta/Elev= 30
       0  680.04     9.6  675.89    19.3   671.4    48.2  657.32    77.1  642.96
    86.7  637.16    96.3  629.93     106  623.24   109.5622.3358   115.6  620.76
   125.2   620.7   129.5621.3982   134.9  622.28   144.5  624.29   154.1  624.96
     183  625.98   221.6  626.73   240.8  626.74   250.5   626.6   269.7  625.97
   298.6  625.69   327.5  625.89   337.2  626.58   346.8  629.04   356.4  634.07
   366.1  640.61   375.7  647.31   385.4  653.06     395  658.23   414.2  668.13
#Mann= 3 , 0 , 0
       0      .1       0   109.5    .045       0   129.5     .07       0
Bank Sta=109.5,129.5
XS Rating Curve= 0 ,0
Exp/Cntr=0.3,0.1

Type RM Length L Ch R = 1 ,1840.8  ,141.6,111,71.7
XS GIS Cut Line= 4
     1815805.626      478112.784     1815852.501      478144.034
     1815978.369      478150.978     1816065.175       478181.36
#Sta/Elev= 25
       0  647.18    18.8  639.78    28.2  636.34    37.6  633.34      47   630.9
    56.3   628.8      66  627.74    75.7  626.51    85.4  624.53    95.1  621.58
   104.8  619.18   114.5  618.43   124.2  619.17   133.9  621.48   143.6  623.25
     163  623.76   172.7  624.17   182.4   624.7   191.6  625.02     210  624.79
   219.2   624.8   237.6  624.56   246.8  624.24   265.2  623.19   274.4   623.1
#Mann= 3 , 0 , 0
       0     .06       0   104.8    .045       0   124.2     .06       0
Bank Sta=104.8,124.2
XS Rating Curve= 0 ,0
Exp/Cntr=0.3,0.1

Type RM Length L Ch R = 1 ,1729.8  ,69.9,71.9,80.3
XS GIS Cut Line= 4
     1815686.442      478258.507     1815848.722      478318.958
      1815929.87      478216.532     1816053.022       478212.61
#Sta/Elev= 30
       0  622.85    28.9  622.05    67.4  621.47    86.6  621.34    96.2  621.53
   115.4   621.7   153.9  621.79   163.6  622.04   173.2  622.58   182.5  622.92
   191.8  623.11   201.2  623.09   210.5  622.62   219.8  621.33   229.2  618.86
   238.5  617.72   247.8  617.09   257.2  617.38   266.5  617.87   275.8  618.86
   285.2  620.38   294.5  622.58   313.3  623.99   322.8  624.03   341.8   623.3
   351.2  623.15   360.7  623.23   389.2  622.76   408.1  622.71   427.1  623.03
#Mann= 3 , 0 , 0
       0     .06       0   238.5    .045       0   266.5     .06       0
#XS Ineff= 2 , 0
          194.18  623.43
Permanent Ineff=
       F       F
Bank Sta=238.5,266.5
XS Rating Curve= 0 ,0
Exp/Cntr=0.3,0.1