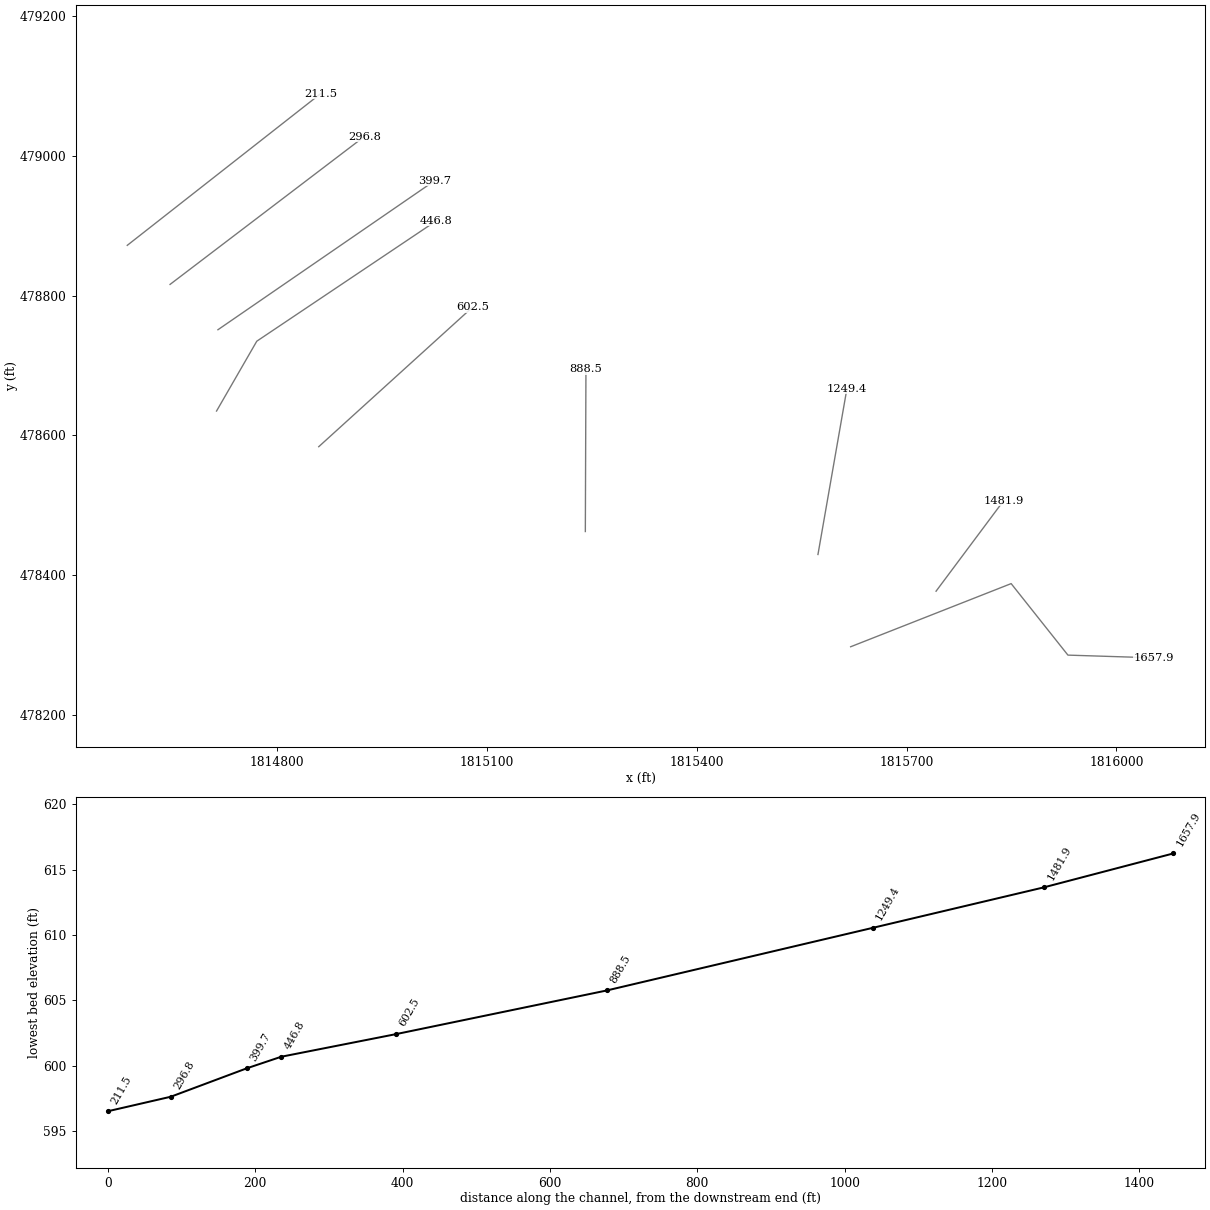
HEC-RAS study SPRINGFORK.prj: SPRINGFORK

--- SPRINGFORK.g01 (geometry) --- (continued)

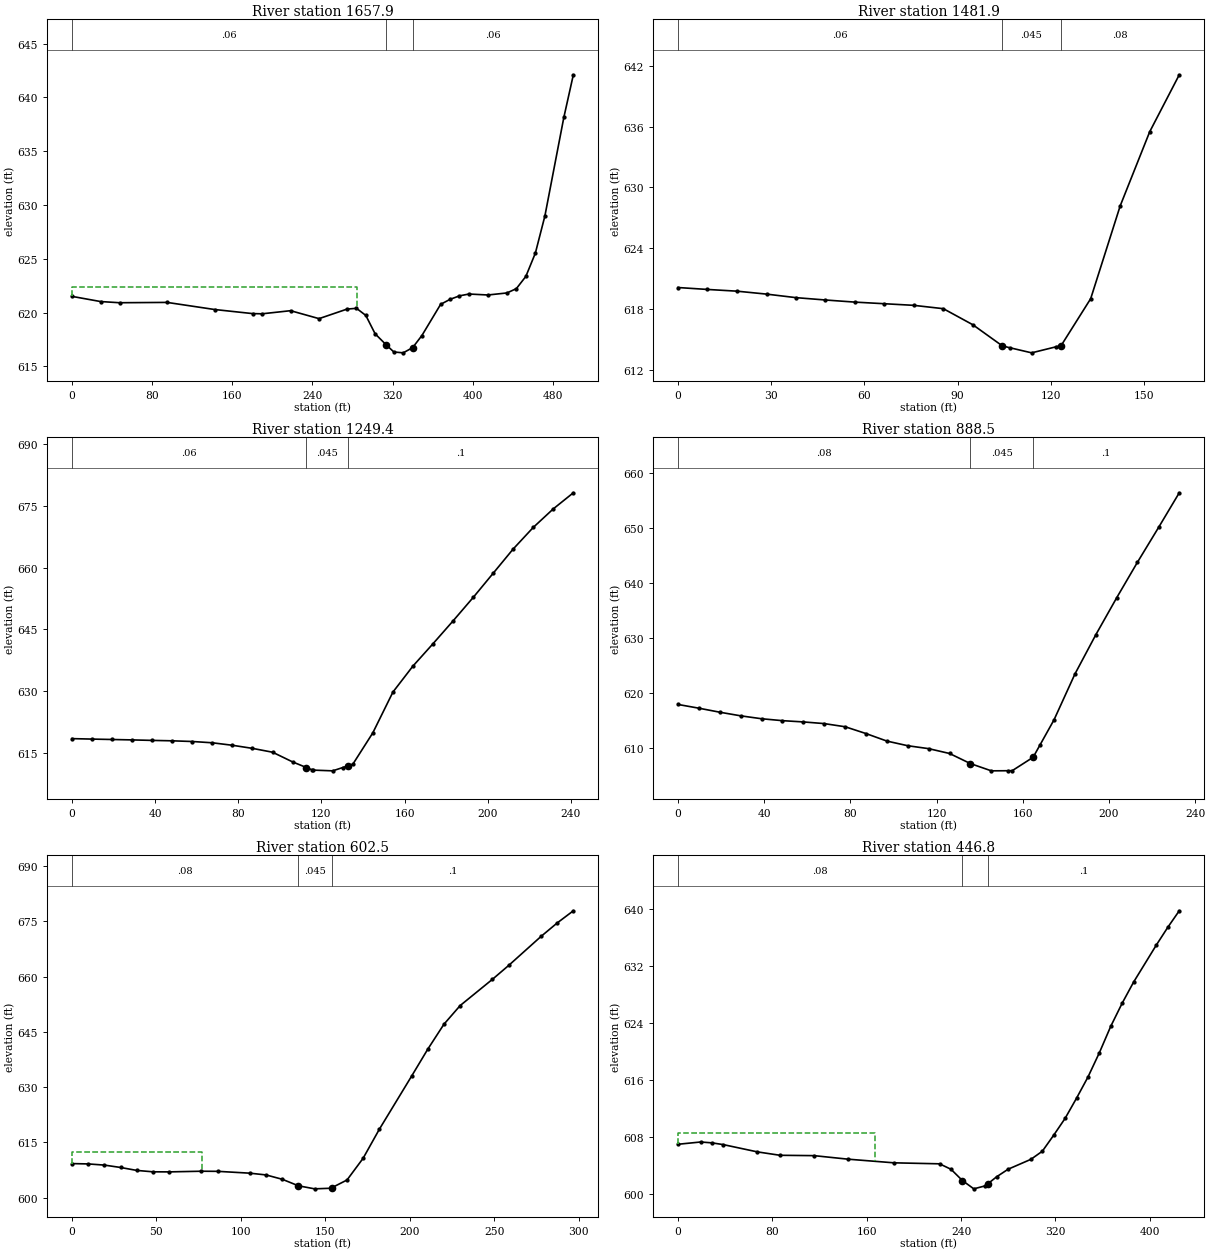
Type RM Length L Ch R = 1 ,1657.9  ,127.6,176,226.7
XS GIS Cut Line= 4
     1815620.146      478297.074      1815849.59      478387.534
     1815930.738      478285.109      1816053.89      478281.187
#Sta/Elev= 30
       0   621.5    28.5  621.02    47.4  620.91    94.9  620.94   142.3  620.28
   180.2   619.9   189.7  619.88   218.2  620.17   246.6  619.43   274.6  620.32
     284  620.39   293.3  619.73   302.6  618.02   313.8  616.98   321.3  616.33
   330.6  616.25     340  616.73   349.3  617.86     368  620.76   377.3  621.22
   386.8  621.55   396.3  621.72   415.2  621.63   434.2  621.82   443.6  622.22
   453.1  623.36   462.6  625.53   472.1  628.98     491  638.14   500.5  642.11
#Mann= 3 , 0 , 0
       0     .06       0   313.8    .045       0     340     .06       0
#XS Ineff= 2 , 0
          284.23  622.35
Permanent Ineff=
       F       F
Bank Sta=313.8,340
XS Rating Curve= 0 ,0
Exp/Cntr=0.3,0.1

Type RM Length L Ch R = 1 ,1481.9  ,221.9,232.4,243
XS GIS Cut Line= 2
     1815742.258      478376.673     1815838.612      478506.013
#Sta/Elev= 21
       0   620.1     9.5  619.91      19  619.74    28.5  619.45      38   619.1
    47.4  618.87    56.9  618.66    66.4   618.5    75.9  618.34    85.4  618.01
    94.9  616.42   104.2 614.374   104.4  614.33   106.7  614.16   113.8  613.65
   121.7  614.25   123.3  614.37   132.8     619   142.3  628.17   151.8  635.49
   161.3  641.11
#Mann= 3 , 0 , 0
       0     .06       0   104.2    .045       0   123.3     .08       0
Bank Sta=104.2,123.3
XS Rating Curve= 0 ,0
Exp/Cntr=0.3,0.1

Type RM Length L Ch R = 1 ,1249.4  ,357,360.9,364.6
XS GIS Cut Line= 2
     1815573.429       478429.25     1815614.846      478666.851
#Sta/Elev= 30
       0  618.39     9.6  618.28    19.3  618.18    28.9  618.08    38.6  617.96
    48.2  617.86    57.9  617.69    67.5  617.38    77.2  616.77    86.8  616.02
    96.5  615.08   106.1  612.73   112.8611.3463   115.3  610.83   115.8  610.73
   125.4  610.55   130.3  611.36   132.8611.7767   135.1  612.16   144.7  619.78
   154.4  629.73     164  636.04   173.6  641.45   183.3  647.03     193  652.75
   202.6  658.63   212.2  664.52   221.9   669.8   231.5   674.3   241.2  678.24
#Mann= 3 , 0 , 0
       0     .06       0   112.8    .045       0   132.8      .1       0
Bank Sta=112.8,132.8
XS Rating Curve= 0 ,0
Exp/Cntr=0.3,0.1

Type RM Length L Ch R = 1 ,888.5   ,304.9,286,267.3
XS GIS Cut Line= 2
      1815240.91      478462.123     1815241.778      478694.762
#Sta/Elev= 27
       0  617.84     9.7  617.16    19.4  616.43    29.1  615.77    38.8  615.24
    48.5  614.89    58.2  614.66    67.8  614.36    77.6  613.78    87.2  612.55
    96.9  611.18   106.6  610.33   116.3   609.8     126  608.92   135.7  607.08
   145.4  605.76   153.1  605.78   155.1  605.79   164.8  608.23   168.1  610.55
   174.5  615.05   184.2  623.39   193.9  630.54   203.6  637.28   213.2  643.72
     223  650.05   232.6  656.36
#Mann= 3 , 0 , 0
       0     .08       0   135.7    .045       0   164.8      .1       0
Bank Sta=135.7,164.8
XS Rating Curve= 0 ,0
Exp/Cntr=0.3,0.1

Type RM Length L Ch R = 1 ,602.5   ,159,155.7,152.4
XS GIS Cut Line= 2
     1814859.833      478583.651     1815079.451      478783.304
#Sta/Elev= 28
       0  609.27     9.6  609.18    19.2  608.86    28.7  608.22    38.3  607.42
    47.9  607.04    57.4  607.02    76.6   607.2    86.2  607.17   105.3  606.67
   114.9  606.19   124.5  605.01     134  603.25   143.6  602.42   153.2  602.58
   153.7   602.7   162.8  604.82   172.3  610.69   181.9  618.56   201.1  633.05
   210.6  640.31   220.2   647.1   229.8  652.16   248.9  659.28   258.5  663.04
   277.7  670.93   287.2  674.56   296.8  677.88
#Mann= 3 , 0 , 0
       0     .08       0     134    .045       0   153.7      .1       0
#XS Ineff= 2 , 0
            76.8  612.35
Permanent Ineff=
       F       F
Bank Sta=134,153.7
XS Rating Curve= 0 ,0
Exp/Cntr=0.3,0.1

Type RM Length L Ch R = 1 ,446.8   ,46.8,47,47.3
XS GIS Cut Line= 3
     1814713.732      478634.726     1814771.249      478734.747
     1815028.236      478907.436
#Sta/Elev= 30
       0  606.96    19.2  607.28    28.8  607.16    38.5  606.91    67.3  605.89
    86.5  605.41   115.4  605.36   144.4  604.86   183.1  604.35   221.8  604.21
   231.5  603.44   241.2  601.85   250.8  600.69   260.5  601.11   262.7   601.4
   270.2  602.39   279.9  603.45   299.2  604.84   308.9  605.98   318.6  608.25
   328.2   610.6   337.9  613.44   347.6  616.42   357.3  619.85   366.9  623.55
   376.6  626.81   386.3  629.78   405.6     635   415.3  637.49     425  639.81
#Mann= 3 , 0 , 0
       0     .08       0   241.2    .045       0   262.7      .1       0
#XS Ineff= 2 , 0
          167.09  608.52
Permanent Ineff=
       F       F
Bank Sta=241.2,262.7
XS Rating Curve= 0 ,0
Exp/Cntr=0.3,0.1

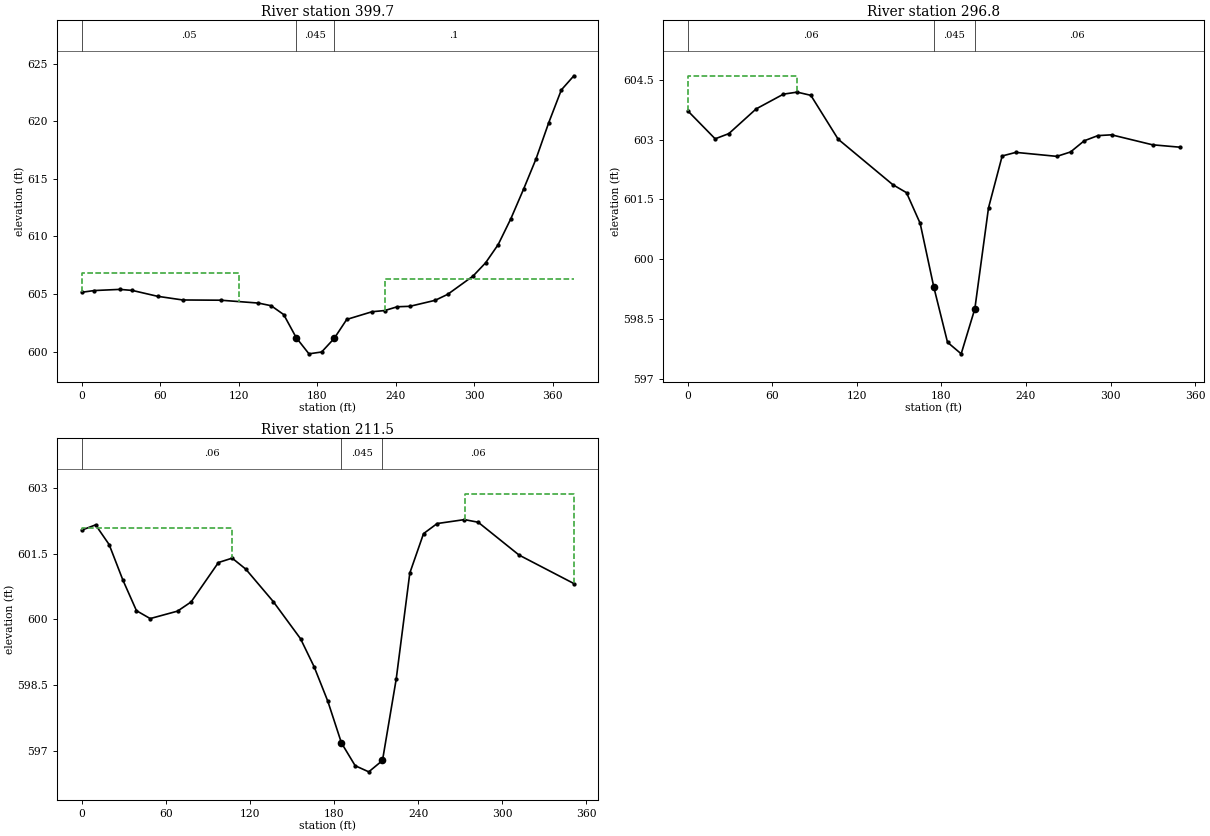
Type RM Length L Ch R = 1 ,399.7   ,101.8,102.9,104
XS GIS Cut Line= 2
     1814715.736      478751.186     1815025.632      478964.728
#Sta/Elev= 30
       0  605.15     9.6   605.3      29   605.4    38.6  605.31    57.9   604.8
    77.2  604.48   106.2  604.46   135.1  604.21   144.8  603.98   154.4  603.21
     164   601.2   173.7   599.8   183.4  599.96     193  601.14   202.6  602.79
     222  603.46   231.6  603.56   241.2  603.89   250.9  603.93   270.2  604.45
   279.8  604.97   299.2  606.56   308.8  607.71   318.4  609.29   328.1  611.54
   337.8   614.1   347.4  616.75     357  619.86   366.7  622.73   376.3  623.96
#Mann= 3 , 0 , 0
       0     .05       0     164    .045       0     193      .1       0
#XS Ineff= 2 , 0
          120.55  606.79  231.53          606.33
Permanent Ineff=
       F       F
Bank Sta=164,193
XS Rating Curve= 0 ,0
Exp/Cntr=0.3,0.1

Type RM Length L Ch R = 1 ,296.8   ,85,85.4,85.7
XS GIS Cut Line= 2
     1814647.281      478816.101     1814924.933      479027.869
#Sta/Elev= 25
       0  603.72    19.4  603.02    29.1  603.15    48.5  603.77    67.9  604.14
    77.6  604.19    87.3  604.11   106.7  603.01   145.5  601.87   155.2  601.67
   164.9   600.9   174.6   599.3   184.3  597.92     194  597.63   203.7  598.76
   213.4  601.29   223.1  602.59   232.8  602.68   261.9  602.58   271.6  602.69
   281.3  602.97     291   603.1   300.7  603.12   329.8  602.87   349.2  602.81
#Mann= 3 , 0 , 0
       0     .06       0   174.6    .045       0   203.7     .06       0
#XS Ineff= 2 , 0
           77.56   604.6
Permanent Ineff=
       F       F
Bank Sta=174.6,203.7
XS Rating Curve= 0 ,0
Exp/Cntr=0.3,0.1

Type RM Length L Ch R = 1 ,211.5   ,205.4,211.5,217.5
XS GIS Cut Line= 2
     1814586.104      478872.049     1814862.186      479089.046
#Sta/Elev= 27
       0  602.04     9.8  602.16    19.5  601.71    29.3   600.9      39   600.2
    48.8  600.02    68.3  600.19      78   600.4    97.5   601.3   107.3   601.4
     117  601.15   136.6  600.41   156.1  599.56   165.8  598.92   175.6  598.13
   185.3  597.18   195.1  596.66   204.8  596.52   214.6  596.78   224.4  598.64
   234.1  601.06   243.9  601.96   253.6  602.19   273.1  602.28   282.9  602.22
   312.1  601.47   351.2  600.82
#Mann= 3 , 0 , 0
       0     .06       0   185.3    .045       0   214.6     .06       0
#XS Ineff= 2 , 0
          106.95  602.09  273.15          602.87
Permanent Ineff=
       F       F
Bank Sta=185.3,214.6
XS Rating Curve= 0 ,0
Exp/Cntr=0.3,0.1

Chan Stop Cuts=-1
Use User Specified Reach Order=0
Composite Channel Slope=5